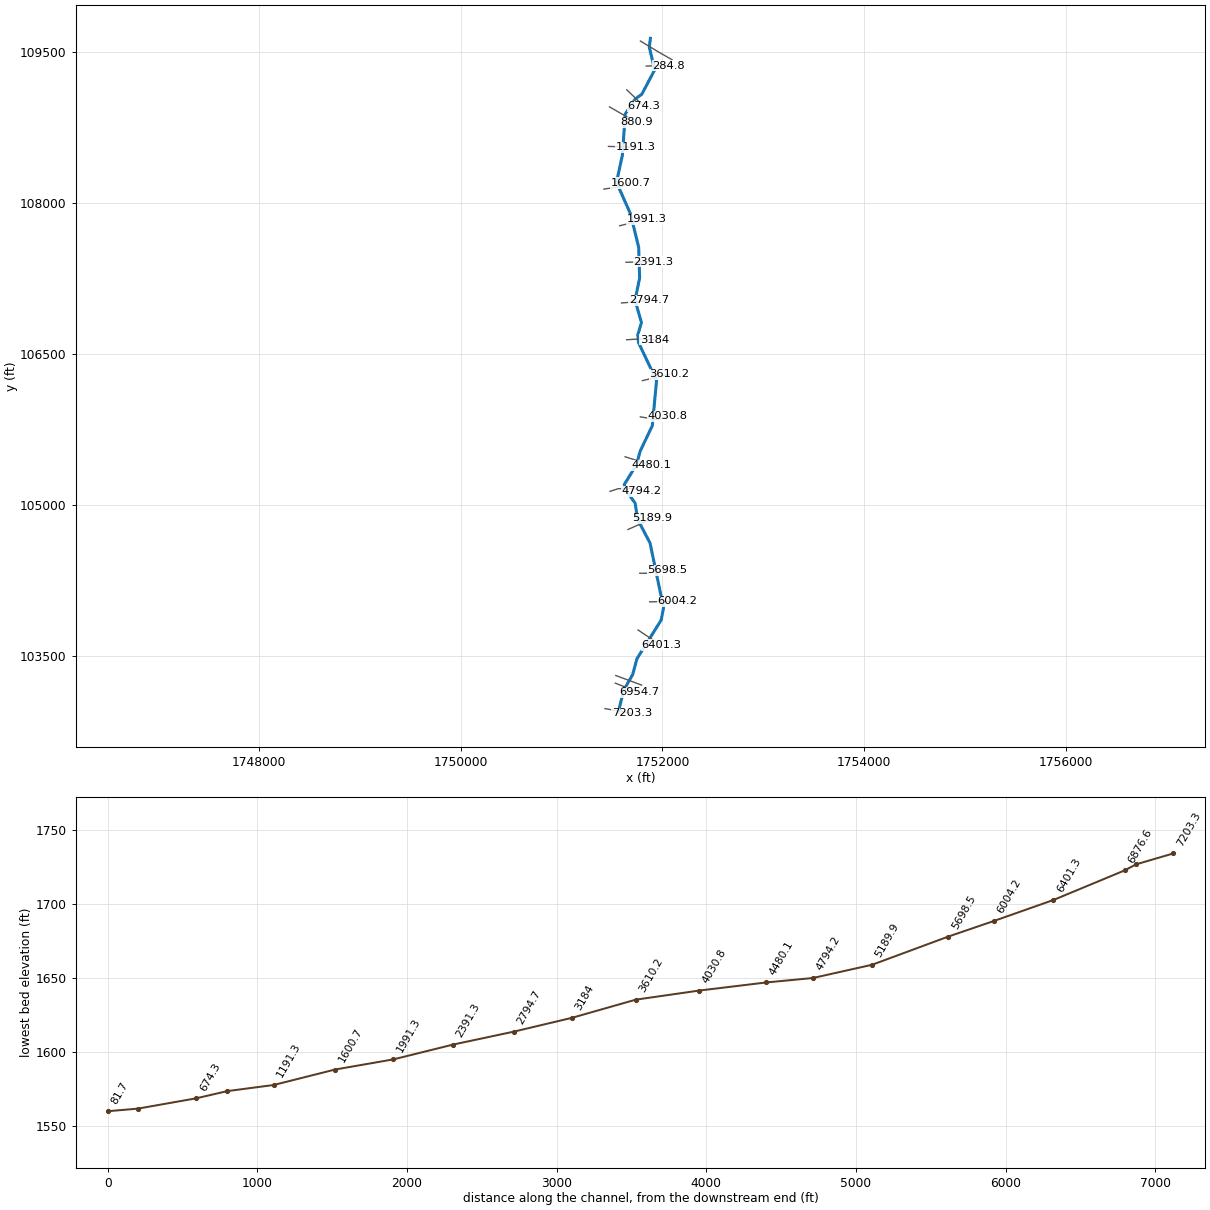
--- Straight Fork.prj (project) ---

Proj Title=Straight Fork
Current Plan=p01
Default Exp/Contr=0,0
English Units
Geom File=g01
Flow File=f01
Plan File=p01
BEGIN DESCRIPTION:
END DESCRIPTION:
DSS Export Rating Curves= 0
DSS Export Rating Curve Sorted= 0
DSS Export Volume Flow Curves= 0
DXF OffsetX= 0
DXF OffsetY= 0
DXF ScaleX= 0
DXF ScaleY= 0

--- Straight Fork.p01 (plan) ---

Plan Title=Floodplain
Program Version=4.00
Geom File=g01
Flow File=f01
K Sum by GR=0
Std Step Tol=0.01
Critical Tol=0.01
Num of Std Step Trials=20
Max Error Tol=0.3
Flow Tol Ratio=0.001
Split Flow NTrial=30
Split Flow Tol=0.02
Split Flow Ratio=0.02
Log Output Level=0
Friction Slope Method=1
Unsteady Friction Slope Method=2
Unsteady Bridges Friction Slope Method=1
Global Log Level=0
CheckData=False
Run HTab=0
Run UNet=0
Run PostProcess=0
UNET Theta=0
UNET Theta Warmup=0
UNET ZTol=0
UNET ZSATol=0
UNET MxIter=0
UNET MaxInSteps=0
UNET DtIC=0
UNET DtMin=0
UNET MaxCRTS=0
UNET WFStab=0
UNET SFStab=0
UNET WFX=0
UNET SFX=0
UNET DSS MLevel=0
UNET DZMax Abort=0
UNET Convert EG Bridges=0
UNET Use Existing IB Tables=0
UNET Froude Limit=0
UNET Froude Power=0
Write IC File=0
Echo Input=False
Echo Output=False
Write Detailed=0

--- Straight Fork.f01 (steady flow) ---

Flow Title=NFF Regression Equation
Program Version=4.00
Number of Profiles=1
Profile Names=P100yr
River Rch & RM=Straight Fork,Main      ,7203.3
534.4018
River Rch & RM=Straight Fork,Main      ,6004.2
592.0251
River Rch & RM=Straight Fork,Main      ,5698.5
664.2593
River Rch & RM=Straight Fork,Main      ,4794.2
675.2137
River Rch & RM=Straight Fork,Main      ,4480.1
759.3050
River Rch & RM=Straight Fork,Main      ,3610.2
816.0429
River Rch & RM=Straight Fork,Main      ,1191.3
863.9023
River Rch & RM=Straight Fork,Main      ,284.8
957.4100
Boundary for River Rch & Prof#=Straight Fork,Main      ,1
Up Type=0
Dn Type=3
Dn Slope=0.018261

--- Straight Fork.g01 (geometry) ---

Geom Title=Geometry
Program Version=4.00

River Reach=Straight Fork   ,Main
Reach XY= 30
      1751562.62      102941.737     1751616.168      103158.925
     1751705.056      103314.647     1751747.012      103470.777
     1751987.381      103855.087     1752011.126      103976.997
     1751877.006      104621.463     1751753.202      104858.066
     1751729.535      105017.794     1751628.711      105157.258
     1751621.833      105204.029     1751742.197      105398.675
     1751779.339      105535.547     1751899.703      105787.969
     1751941.659      106236.414     1751762.006       106615.28
     1751755.626      106691.845     1751791.722       106812.66
     1751728.441      107035.635     1751773.855      107256.055
     1751764.207      107561.801     1751683.047      107893.319
     1751544.186      108207.568     1751602.574      108475.884
     1751631.462      108887.876     1751731.015      109037.098
     1751795.731      109083.584     1751923.454      109325.939
     1751869.676      109550.333     1751880.598      109638.868

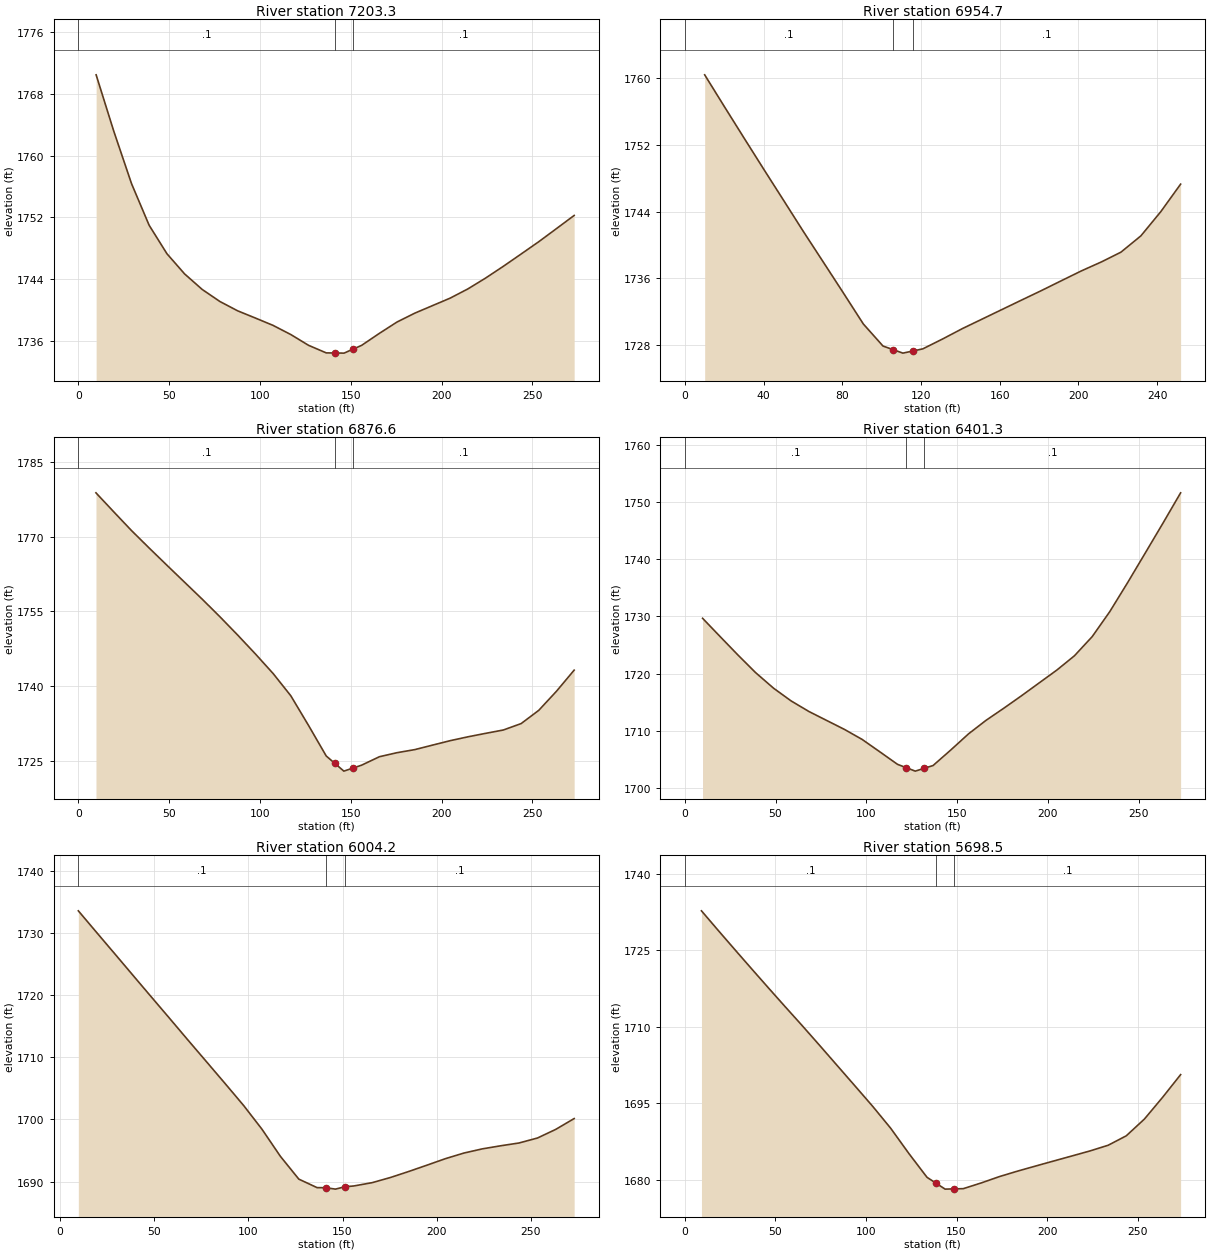
Type RM Length L Ch R = 1 ,7203.3  ,252.6,248.6,244.6
XS GIS Cut Line= 3
     1751429.935      102975.307     1751564.358      102951.584
      1751698.78      102927.862
#Sta/Elev= 30
     9.8 1770.48    19.5 1763.18    29.3 1756.36      39 1750.96    48.8 1747.27
    58.5 1744.66    68.2 1742.64      78 1741.07    87.7 1739.87    97.5 1738.93
   107.2 1737.98     117 1736.79   126.7  1735.4   136.5 1734.41   141.2  1734.4
   146.3 1734.38   151.2 1734.89     156 1735.39   165.8 1736.95   175.5 1738.42
   185.3 1739.57     195 1740.54   204.7 1741.51   214.5 1742.71   224.2 1744.11
     234 1745.64   243.7 1747.22   253.5 1748.83   263.2 1750.52     273 1752.24
#Mann= 3 , 0 , 0
       0      .1       0   141.2    .045       0   151.2      .1       0
Bank Sta=141.2,151.2
XS Rating Curve= 0 ,0
Exp/Cntr=0.3,0.1

Type RM Length L Ch R = 1 ,6954.7  ,77.6,78.1,78.5
XS GIS Cut Line= 2
     1751532.562       103228.27     1751766.773      103135.634
#Sta/Elev= 27
    10.1 1760.43    20.1 1756.62    30.2 1752.81    40.3 1749.03    50.4 1745.29
    60.4 1741.57    70.5 1737.91    80.6 1734.24    90.7 1730.53   100.7 1727.88
   105.8 1727.45   110.8 1727.03   115.8 1727.28   120.9 1727.54     131 1728.73
     141 1729.97   151.1 1731.12   161.2 1732.27   171.3 1733.42   181.3 1734.55
   191.4 1735.73   201.5  1736.9   211.6 1737.97   221.6 1739.15   231.7  1741.1
   241.8    1744   251.9 1747.31
#Mann= 3 , 0 , 0
       0      .1       0   105.8    .045       0   115.8      .1       0
Bank Sta=105.8,115.8
XS Rating Curve= 0 ,0
Exp/Cntr=0.3,0.1

Type RM Length L Ch R = 1 ,6876.6  ,480.3,475.3,471
XS GIS Cut Line= 3
     1751537.566       103304.03     1751665.569      103256.622
     1751793.572      103209.214
#Sta/Elev= 30
     9.7 1778.84    19.5 1775.02    29.2 1771.28      39 1767.74    48.8 1764.27
    58.5 1760.86    68.3 1757.42      78  1753.9    87.7 1750.25    97.5 1746.44
   107.3 1742.48     117 1738.02   126.8 1732.03   136.5 1725.91   141.2 1724.44
   146.2 1722.87   151.2 1723.48     156 1724.07   165.8 1725.77   175.5 1726.58
   185.3  1727.2     195  1728.1   204.8    1729   214.5 1729.77   224.3 1730.47
     234 1731.14   243.8 1732.43   253.5 1735.09   263.3 1738.95     273 1743.18
#Mann= 3 , 0 , 0
       0      .1       0   141.2    .045       0   151.2      .1       0
Bank Sta=141.2,151.2
XS Rating Curve= 0 ,0
Exp/Cntr=0.3,0.1

Type RM Length L Ch R = 1 ,6401.3  ,384.7,397.1,408.9
XS GIS Cut Line= 3
      1751757.91      103757.181     1751871.243      103680.587
      1751986.63      103607.828
#Sta/Elev= 30
     9.8 1729.66    19.5 1726.45    29.3 1723.23    39.1 1720.13    48.9 1717.43
    58.6  1715.2    68.4 1713.35    78.2 1711.78    87.9 1710.23    97.7 1708.47
   107.5 1706.29   117.2 1704.11     122 1703.52     127 1702.92     132 1703.42
   136.8  1703.9   146.5  1706.6   156.3 1709.43     166 1711.81   175.8 1713.93
   185.5  1716.1   195.2 1718.34     205  1720.6   214.7  1723.1   224.5 1726.46
   234.2 1730.84     244  1735.9   253.7 1741.07   263.5 1746.32   273.2 1751.61
#Mann= 3 , 0 , 0
       0      .1       0     122    .045       0     132      .1       0
Bank Sta=122,132
XS Rating Curve= 0 ,0
Exp/Cntr=0.3,0.1

Type RM Length L Ch R = 1 ,6004.2  ,303.2,305.7,308.2
XS GIS Cut Line= 3
     1751873.268      104036.409     1752009.734      104039.451
       1752146.2      104042.493
#Sta/Elev= 30
     9.7 1733.65    19.5 1730.13    29.3 1726.63      39 1723.15    48.7 1719.68
    58.5 1716.19    68.2 1712.71      78 1709.23    87.8 1705.74    97.5 1702.25
   107.2 1698.44     117 1694.06   126.8 1690.38   136.5 1689.01   141.2    1689
  146.21 1688.77   151.2 1689.15     156 1689.28   165.7 1689.81   175.5 1690.65
   185.2 1691.62     195 1692.65   204.7 1693.69   214.5 1694.59   224.2 1695.26
     234 1695.76   243.7 1696.21   253.5 1697.01   263.2  1698.4     273 1700.15
#Mann= 3 , 0 , 0
     9.7      .1       0   141.2    .045       0   151.2      .1       0
Bank Sta=141.2,151.2
XS Rating Curve= 0 ,0
Exp/Cntr=0.3,0.1

Type RM Length L Ch R = 1 ,5698.5  ,503.1,508.6,514.1
XS GIS Cut Line= 3
     1751775.261      104321.151     1751848.922      104320.671
      1752046.71      104350.293
#Sta/Elev= 30
     9.2 1732.75    18.4 1728.93    27.6 1725.16    36.8 1721.42      46 1717.71
    55.2 1714.04    64.5 1710.37    73.7 1706.67    83.7  1702.6    93.7 1698.53
   103.7 1694.44   113.7 1690.11   123.7 1685.18   133.7 1680.52   138.7 1679.36
   143.7  1678.2   148.7 1678.25   153.7 1678.29   163.7 1679.42   173.7 1680.66
   183.7 1681.73   193.7 1682.73   203.7 1683.72   213.7  1684.7   223.7 1685.69
   233.7  1686.8   243.7 1688.65   253.7 1691.93   263.7 1696.17   273.7 1700.64
#Mann= 3 , 0 , 0
       0      .1       0   138.7    .045       0   148.7      .1       0
Bank Sta=138.7,148.7
XS Rating Curve= 0 ,0
Exp/Cntr=0.3,0.1

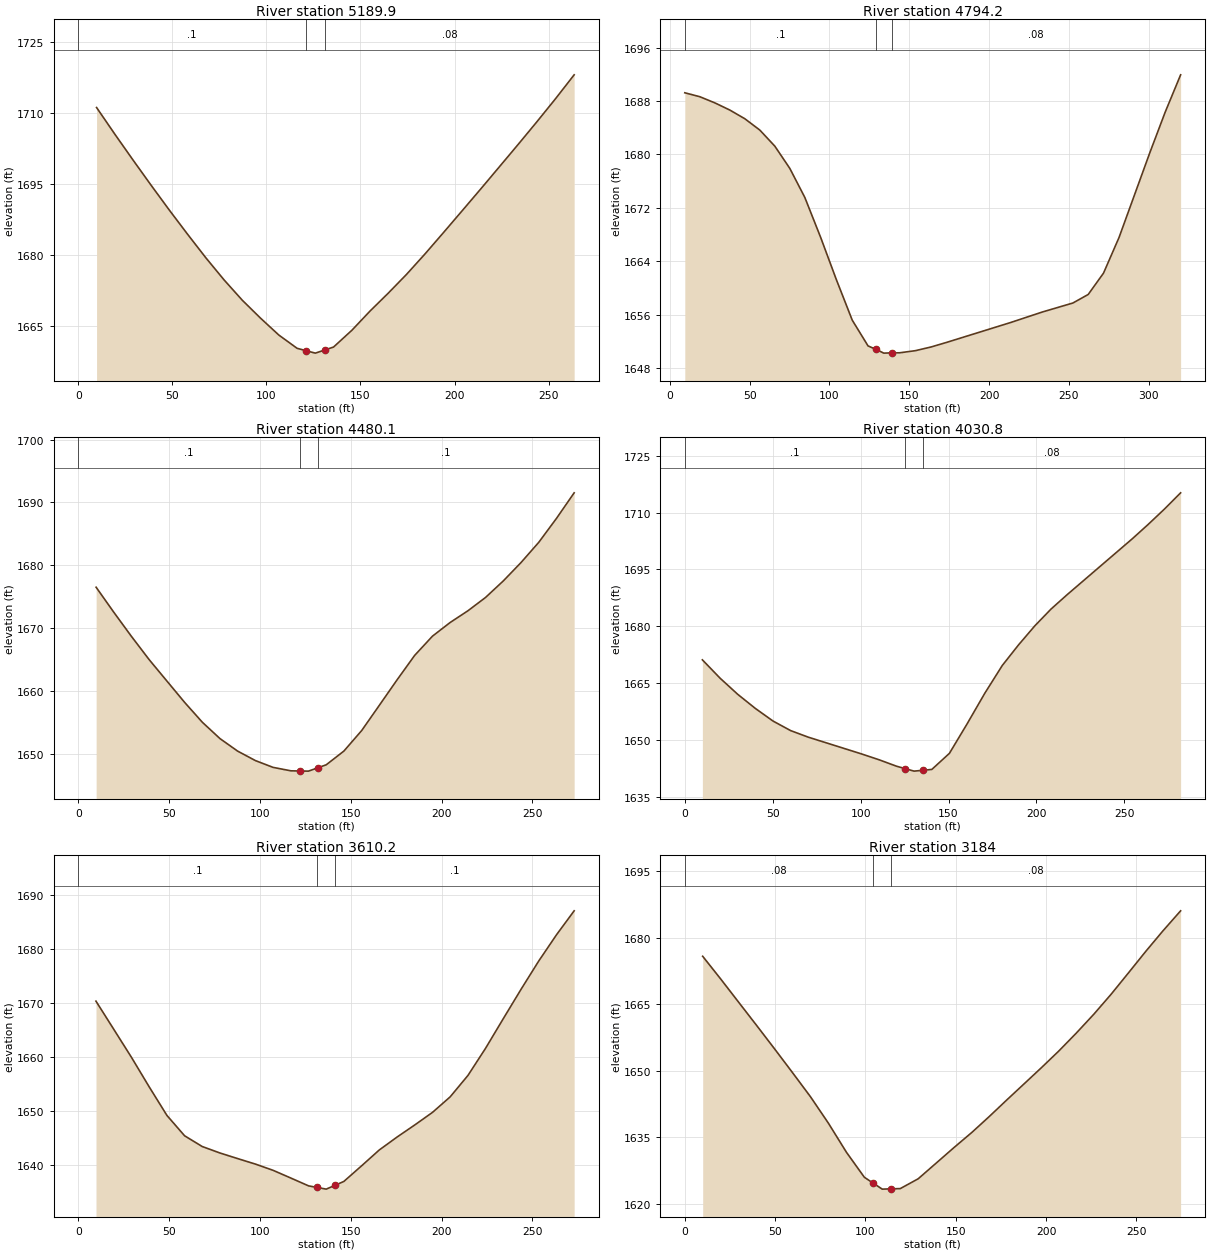
Type RM Length L Ch R = 1 ,5189.9  ,403.9,395.8,387.5
XS GIS Cut Line= 3
     1751658.407      104755.884      1751817.46      104827.545
     1751897.905      104865.937
#Sta/Elev= 29
     9.7  1711.1    19.4 1705.47    29.1 1699.99    38.8 1694.61    48.5 1689.35
    58.2 1684.25    67.8 1679.33    77.5 1674.65    87.2 1670.35    96.9 1666.56
   106.6    1663   116.3  1660.2     121  1659.7     126 1659.18     131 1659.84
   135.7 1660.47   145.4    1664   155.1 1668.08   164.8 1671.87   174.5 1675.83
   184.4 1680.19   194.3 1684.74   204.2 1689.34   214.1 1693.96     224 1698.64
   233.9 1703.33   243.8 1708.09   253.7 1712.96   263.6 1718.01
#Mann= 3 , 0 , 0
       0      .1       0     121    .045       0     131     .08       0
Bank Sta=121,131
XS Rating Curve= 0 ,0
Exp/Cntr=0.3,0.1

Type RM Length L Ch R = 1 ,4794.2  ,320.9,314,307.4
XS GIS Cut Line= 4
     1751480.127      105135.165     1751560.528      105161.383
     1751709.094      105164.879     1751791.243      105136.913
#Sta/Elev= 29
     9.4 1689.25    18.8 1688.66    28.2 1687.74    37.6 1686.66      47 1685.36
    56.4 1683.66    65.8 1681.25    75.2 1677.91    84.6 1673.56    94.5 1667.58
   104.4 1661.21   114.3 1655.17   124.2 1651.31   129.1  1650.8  134.06 1650.23
   139.1 1650.27     144 1650.28   153.9  1650.6   163.8 1651.16   173.7 1651.86
   213.4 1654.81   233.2 1656.38   252.5 1657.74   262.1 1659.02   271.7 1662.22
   281.4 1667.55   300.7 1680.26   310.3 1686.33     320 1691.94
#Mann= 3 , 0 , 0
     9.4      .1       0   129.1    .045       0   139.1     .08       0
Bank Sta=129.1,139.1
XS Rating Curve= 0 ,0
Exp/Cntr=0.3,0.1

Type RM Length L Ch R = 1 ,4480.1  ,446.3,449.3,452.3
XS GIS Cut Line= 3
     1751629.752      105478.981     1751759.688      105437.162
     1751889.625      105395.343
#Sta/Elev= 30
     9.8 1676.49    19.5 1672.52    29.3 1668.64      39 1664.96    48.8 1661.54
    58.5 1658.16    68.3 1654.98      78 1652.38    87.7 1650.39    97.5 1648.88
   107.2  1647.8     117 1647.25   121.8 1647.22   126.7  1647.2   131.8 1647.72
   136.5 1648.21   146.2 1650.39     156 1653.66   165.7 1657.67   175.5 1661.74
   185.2 1665.64     195  1668.7   204.7 1670.87   214.5 1672.74   224.2 1674.86
     234  1677.5   243.7 1680.41   253.5 1683.64   263.2 1687.43     273 1691.53
#Mann= 3 , 0 , 0
       0      .1       0   121.8    .045       0   131.8      .1       0
Bank Sta=121.8,131.8
XS Rating Curve= 0 ,0
Exp/Cntr=0.3,0.1

Type RM Length L Ch R = 1 ,4030.8  ,412.7,420.6,428.5
XS GIS Cut Line= 3
     1751780.789      105875.667     1751959.036      105846.537
      1752053.92      105882.364
#Sta/Elev= 26
      10 1671.12    20.1 1666.26    30.1 1662.01    40.1 1658.29    50.2 1654.94
    60.2 1652.42    70.2 1650.69   100.3 1646.29   110.4 1644.73   120.4 1643.01
   125.4 1642.36   130.4 1641.71   135.4 1641.93   140.5 1642.16   150.5 1646.41
   160.5 1654.15   170.6 1662.27   180.6 1669.65   189.8 1675.06   199.1 1680.12
   208.3 1684.54   217.5 1688.36   254.4 1703.07   263.6 1706.93   272.8 1710.97
     282 1715.26
#Mann= 3 , 0 , 0
       0      .1       0   125.4    .045       0   135.4     .08       0
Bank Sta=125.4,135.4
XS Rating Curve= 0 ,0
Exp/Cntr=0.3,0.1

Type RM Length L Ch R = 1 ,3610.2  ,429.6,426.2,422.8
XS GIS Cut Line= 3
     1751801.537      106235.963     1751934.408      106267.227
      1752067.28      106298.491
#Sta/Elev= 30
     9.7 1670.36    19.5 1665.16    29.2    1660      39 1654.52    48.8 1649.22
    58.5 1645.47    68.2 1643.48      78 1642.28    87.7 1641.25    97.5 1640.23
   107.3 1639.07     117 1637.65   126.8  1636.2   131.5 1635.91   136.5  1635.6
   141.5 1636.33   146.2 1637.02     156 1639.92   165.7 1642.84   175.5 1645.23
   185.3 1647.48     195 1649.79   204.7 1652.65   214.5 1656.61   224.2 1661.63
     234 1667.13   243.8 1672.57   253.5 1677.78   263.3 1682.64     273 1687.06
#Mann= 3 , 0 , 0
       0      .1       0   131.5    .045       0   141.5      .1       0
Bank Sta=131.5,141.5
XS Rating Curve= 0 ,0
Exp/Cntr=0.3,0.1

Type RM Length L Ch R = 1 ,3184    ,388.4,389.3,390.2
XS GIS Cut Line= 3
     1751644.771      106642.142     1751803.478      106652.292
     1751918.413      106641.553
#Sta/Elev= 30
     9.9 1675.87    19.9 1670.73    29.8 1665.51    39.8 1660.25    49.7 1654.98
    59.6 1649.64    69.6 1644.17    79.5 1638.22    89.5 1631.65    99.4 1626.02
   104.3 1624.69   109.3 1623.34   114.3  1623.4   119.3 1623.46   129.2 1625.67
   139.2 1629.22   149.1 1632.74     159 1636.16   168.7 1639.77   178.3 1643.47
   187.9 1647.11   197.5 1650.76   207.1 1654.51   216.7 1658.52   226.4 1662.77
     236 1667.29   245.6 1672.11   255.2 1676.97   264.8 1681.64   274.5 1686.12
#Mann= 3 , 0 , 0
       0     .08       0   104.3    .045       0   114.3     .08       0
Bank Sta=104.3,114.3
XS Rating Curve= 0 ,0
Exp/Cntr=0.3,0.1

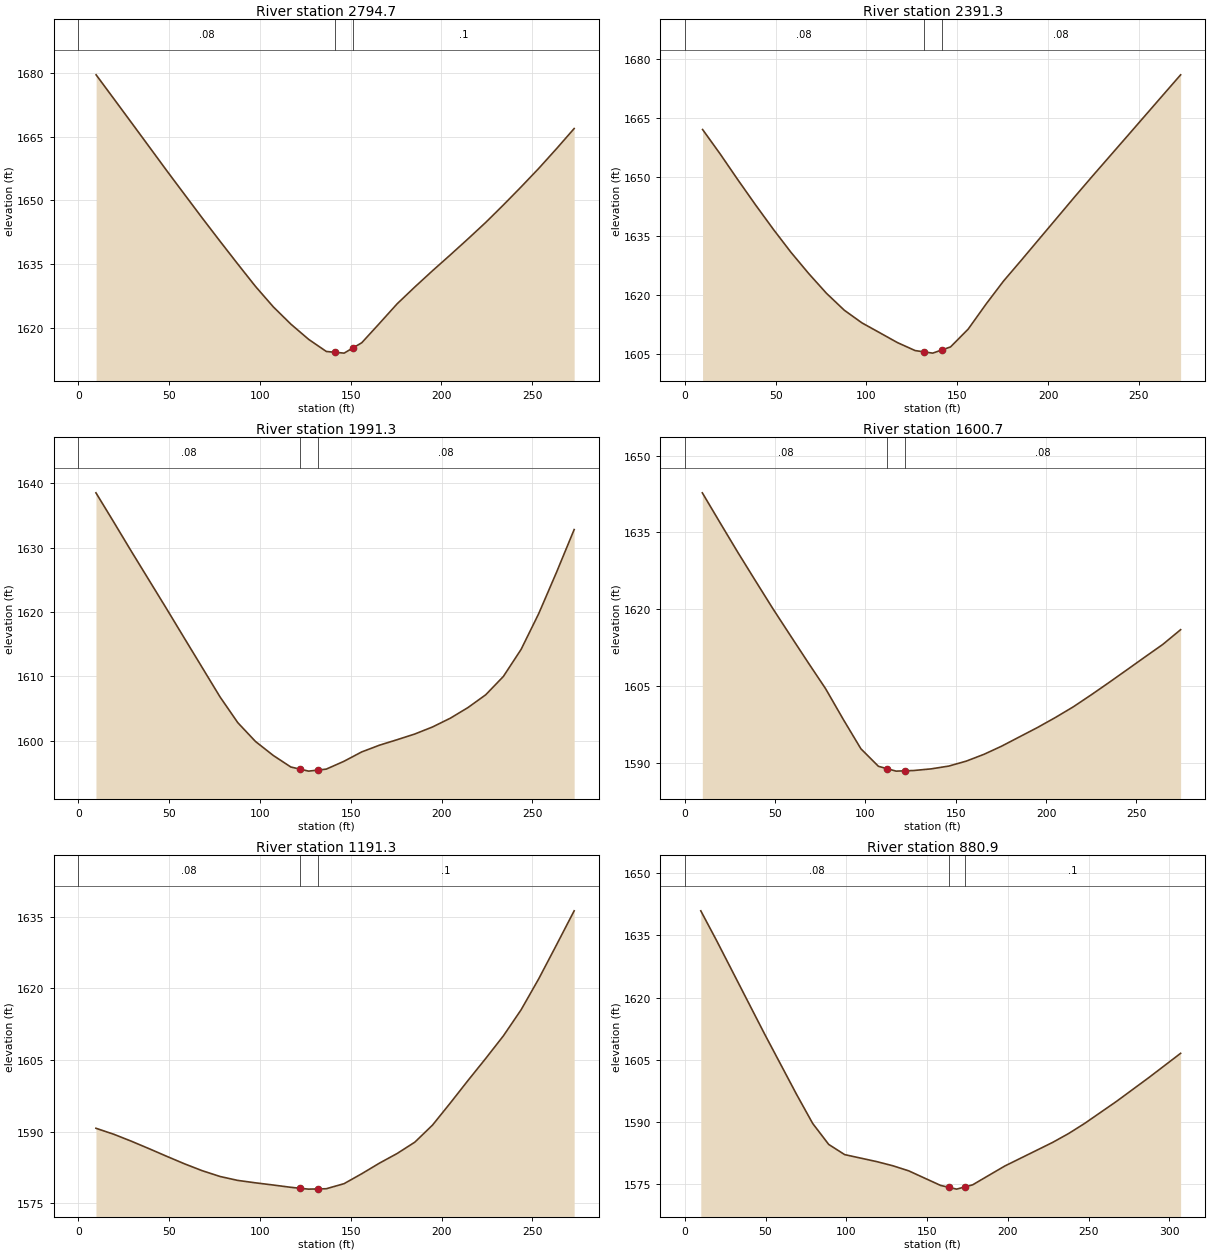
Type RM Length L Ch R = 1 ,2794.7  ,405,403.4,401.8
XS GIS Cut Line= 3
     1751594.305      107007.981     1751691.616      107015.844
     1751866.124      107034.113
#Sta/Elev= 30
     9.8 1679.57    19.5 1673.96    29.3 1668.28    39.1 1662.58    48.8 1656.93
    58.6 1651.33    68.3  1645.8    78.1 1640.33    87.9 1634.94    97.6  1629.7
   107.4 1624.89   117.1 1620.81   126.9 1617.22   136.6 1614.38   141.4 1614.19
   146.4 1613.99   151.4 1615.25   156.1 1616.43   165.9 1621.01   175.6 1625.61
   185.4  1629.6   195.1 1633.41   204.9 1637.14   214.6  1640.9   224.4 1644.79
   234.1 1648.89   243.8 1653.12   253.6 1657.52   263.3 1662.12   273.1 1666.91
#Mann= 3 , 0 , 0
       0     .08       0   141.4    .045       0   151.4      .1       0
Bank Sta=141.4,151.4
XS Rating Curve= 0 ,0
Exp/Cntr=0.3,0.1

Type RM Length L Ch R = 1 ,2391.3  ,395.8,400,404.2
XS GIS Cut Line= 3
     1751638.817      107412.517     1751775.265      107416.282
     1751911.713      107420.046
#Sta/Elev= 30
     9.8 1662.01    19.5  1655.8    29.2 1649.28      39 1642.87    48.8 1636.68
    58.5 1630.85    68.3 1625.45      78 1620.48    87.8  1616.2    97.5 1612.99
   107.3 1610.49     117    1608   126.8 1605.96   131.5 1605.64   136.5 1605.31
   141.5 1606.11   146.3 1606.88     156 1611.38   165.8  1617.7   175.5 1623.59
   185.3 1628.87     195 1634.18   204.8 1639.54   214.5 1644.85   224.2 1650.06
     234 1655.24   243.8 1660.42   253.5 1665.56   263.2  1670.7     273 1675.88
#Mann= 3 , 0 , 0
       0     .08       0   131.5    .045       0   141.5     .08       0
Bank Sta=131.5,141.5
XS Rating Curve= 0 ,0
Exp/Cntr=0.3,0.1

Type RM Length L Ch R = 1 ,1991.3  ,392.4,390.6,388.8
XS GIS Cut Line= 3
     1751575.833      107775.685     1751708.446       107808.03
     1751841.058      107840.374
#Sta/Elev= 30
     9.7 1638.52    19.5 1633.98    29.2 1629.43      39 1624.92    48.8 1620.41
    58.5 1615.88    68.3 1611.33      78 1606.82    87.8 1602.81    97.5  1599.9
   107.3 1597.72     117 1595.92   121.8 1595.61   126.8 1595.28   131.8 1595.44
   136.5 1595.59   146.2  1596.8     156 1598.26   165.8 1599.31   175.5 1600.16
   185.3 1601.05     195 1602.14   204.8  1603.5   214.5 1605.15   224.3 1607.14
     234 1609.98   243.8  1614.2   253.5 1619.76   263.3 1626.18     273 1632.81
#Mann= 3 , 0 , 0
       0     .08       0   121.8    .045       0   131.8     .08       0
Bank Sta=121.8,131.8
XS Rating Curve= 0 ,0
Exp/Cntr=0.3,0.1

Type RM Length L Ch R = 1 ,1600.7  ,412.9,409.4,405.9
XS GIS Cut Line= 3
      1751419.38      108140.006     1751602.476      108167.672
      1751685.62      108200.396
#Sta/Elev= 30
     9.7 1642.72    19.5  1636.9    29.2  1631.2      39 1625.62    48.7 1620.15
    58.5 1614.85    68.2 1609.64      78 1604.47    87.7 1598.53    97.5 1592.77
   107.2 1589.35     112 1588.89     117 1588.41     122 1588.47   126.7 1588.53
   136.4 1588.85   146.2  1589.4   155.9 1590.37   165.7  1591.7   175.4 1593.28
   185.2 1595.08   195.1 1596.89     205 1598.84     215 1600.94   224.9 1603.27
   234.8 1605.69   244.7 1608.16   254.7 1610.67   264.6 1613.13   274.5 1616.01
#Mann= 3 , 0 , 0
       0     .08       0     112    .045       0     122     .08       0
Bank Sta=112,122
XS Rating Curve= 0 ,0
Exp/Cntr=0.3,0.1

Type RM Length L Ch R = 1 ,1191.3  ,320.6,310.4,300.2
XS GIS Cut Line= 3
     1751464.833      108564.178     1751601.292      108560.834
     1751737.755      108557.665
#Sta/Elev= 30
     9.7 1590.72    19.5 1589.47    29.2 1588.01      39 1586.44    48.8 1584.83
    58.5 1583.27    68.2 1581.84      78 1580.63    87.7 1579.81    97.5  1579.3
   107.3 1578.84     117 1578.36   121.8 1578.17   126.7 1577.98   131.8 1578.02
   136.5 1578.06   146.3 1579.12     156 1581.19   165.7  1583.4   175.5 1585.43
   185.3 1587.82     195 1591.38   204.8    1596   214.5  1600.7   224.3 1605.33
     234 1610.05   243.8 1615.53   253.5 1622.01   263.3 1629.12     273 1636.24
#Mann= 3 , 0 , 0
       0     .08       0   121.8    .045       0   131.8      .1       0
Bank Sta=121.8,131.8
XS Rating Curve= 0 ,0
Exp/Cntr=0.3,0.1

Type RM Length L Ch R = 1 ,880.9   ,211.4,206.6,201.7
XS GIS Cut Line= 2
     1751474.883      108957.696     1751740.555      108803.886
#Sta/Elev= 22
     9.9 1640.88    19.8 1633.63    49.5 1611.14    69.3  1596.6    79.2 1589.66
    89.1 1584.62      99 1582.16   118.8 1580.48   128.7 1579.49   138.6 1578.26
   158.4 1574.74   163.3  1574.3   168.3 1573.85   173.3 1574.37   178.2 1574.88
   198.1 1579.41   227.8 1585.11   237.7 1587.25   247.6 1589.68   267.4 1595.01
   287.2 1600.68     307 1606.56
#Mann= 3 , 0 , 0
       0     .08       0   163.3    .045       0   173.3      .1       0
Bank Sta=163.3,173.3
XS Rating Curve= 0 ,0
Exp/Cntr=0.3,0.1

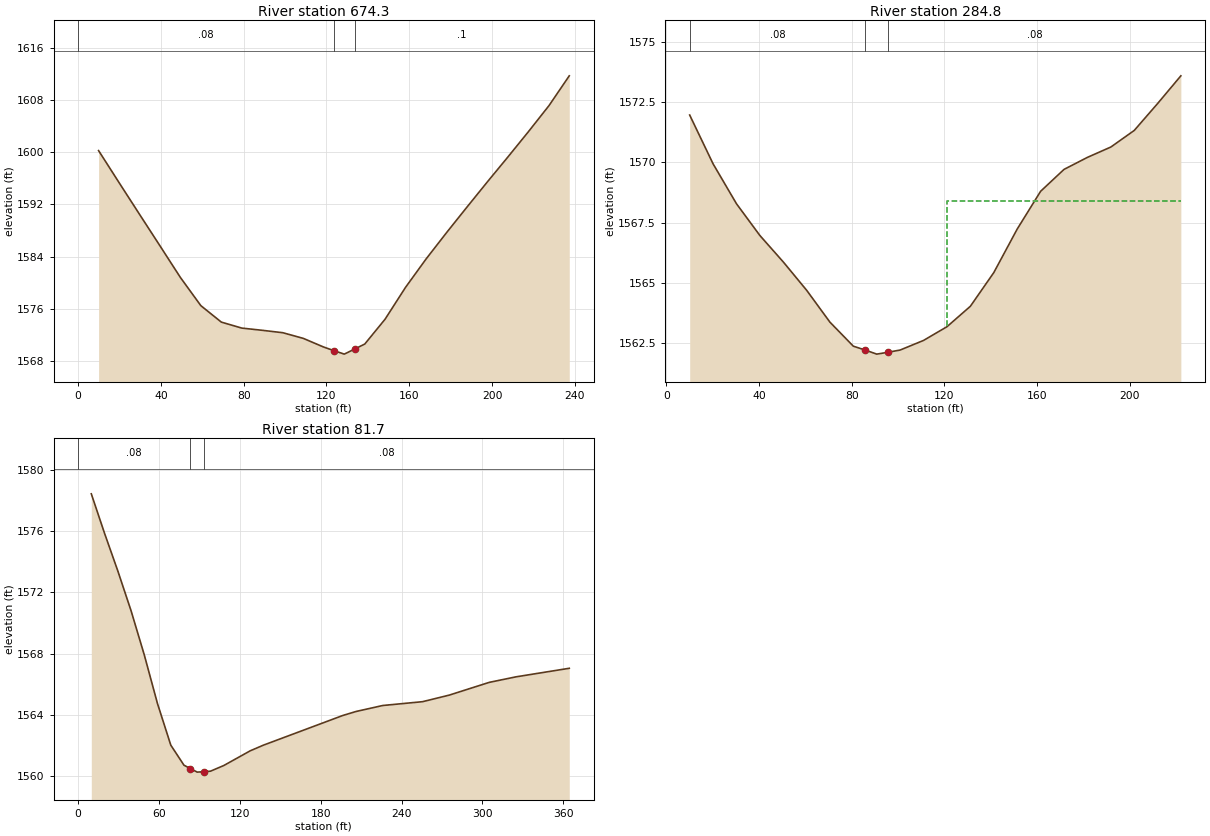
Type RM Length L Ch R = 1 ,674.3   ,373.8,389.6,405.4
XS GIS Cut Line= 2
     1751646.172      109127.237      1751817.46       108962.94
#Sta/Elev= 26
     9.9 1600.27    19.8 1595.35    29.7 1590.47    39.6 1585.62    49.4 1580.79
    59.3 1576.45    69.2 1573.92    79.1    1573      89 1572.66    98.9 1572.29
   108.8 1571.42   118.7 1570.08   123.6 1569.54   128.6    1569   133.6 1569.78
   138.5 1570.55   148.3 1574.36   158.2 1579.26   168.1 1583.61     178 1587.66
   187.9  1591.6   197.8 1595.49   207.7 1599.31   217.6 1603.19   227.5 1607.18
   237.3 1611.76
#Mann= 3 , 0 , 0
       0     .08       0   123.6    .045       0   133.6      .1       0
Bank Sta=123.6,133.6
XS Rating Curve= 0 ,0
Exp/Cntr=0.3,0.1

Type RM Length L Ch R = 1 ,284.8   ,215.1,203,190.1
XS GIS Cut Line= 2
     1751838.435      109363.196      1752060.41      109368.439
#Sta/Elev= 24
    10.1 1571.97    20.2 1569.94    30.3 1568.28    40.4 1566.96    50.5 1565.86
    60.6 1564.68    70.6 1563.36    80.7 1562.36    85.8  1562.2    90.8 1562.03
    95.8 1562.11   100.9  1562.2     111  1562.6   121.1 1563.17   131.2 1564.02
   141.3 1565.42   151.4 1567.23   161.5  1568.8   171.6 1569.71   181.7 1570.21
   191.8 1570.64   201.9 1571.33   211.9 1572.44     222  1573.6
#Mann= 3 , 0 , 0
    10.1     .08       0    85.8    .045       0    95.8     .08       0
#XS Ineff= 2 , 0
                          121.22         1568.38
Permanent Ineff=
       F       F
Bank Sta=85.8,95.8
XS Rating Curve= 0 ,0
Exp/Cntr=0.3,0.1

Type RM Length L Ch R = 1 ,81.7    ,75.3,81.7,89
XS GIS Cut Line= 3
     1751781.653      109611.591     1751958.305      109505.069
     1752095.367      109426.118
#Sta/Elev= 23
     9.8 1578.43    19.6 1575.86    29.5 1573.39    39.3  1570.8    49.1 1567.92
    58.9 1564.74    68.8 1562.02    78.6 1560.71    83.4 1560.49    88.4 1560.26
    93.4 1560.29    98.2 1560.32   108.1 1560.69   127.7 1561.65   137.5 1562.02
   196.5 1563.96   206.3 1564.22   226.1 1564.61   255.7 1564.86   275.5 1565.29
   305.1 1566.12   324.9 1566.48   364.5 1567.04
#Mann= 3 , 0 , 0
       0     .08       0    83.4    .045       0    93.4     .08       0
Bank Sta=83.4,93.4
XS Rating Curve= 0 ,0
Exp/Cntr=0.3,0.1

Chan Stop Cuts=-1
Use User Specified Reach Order=0